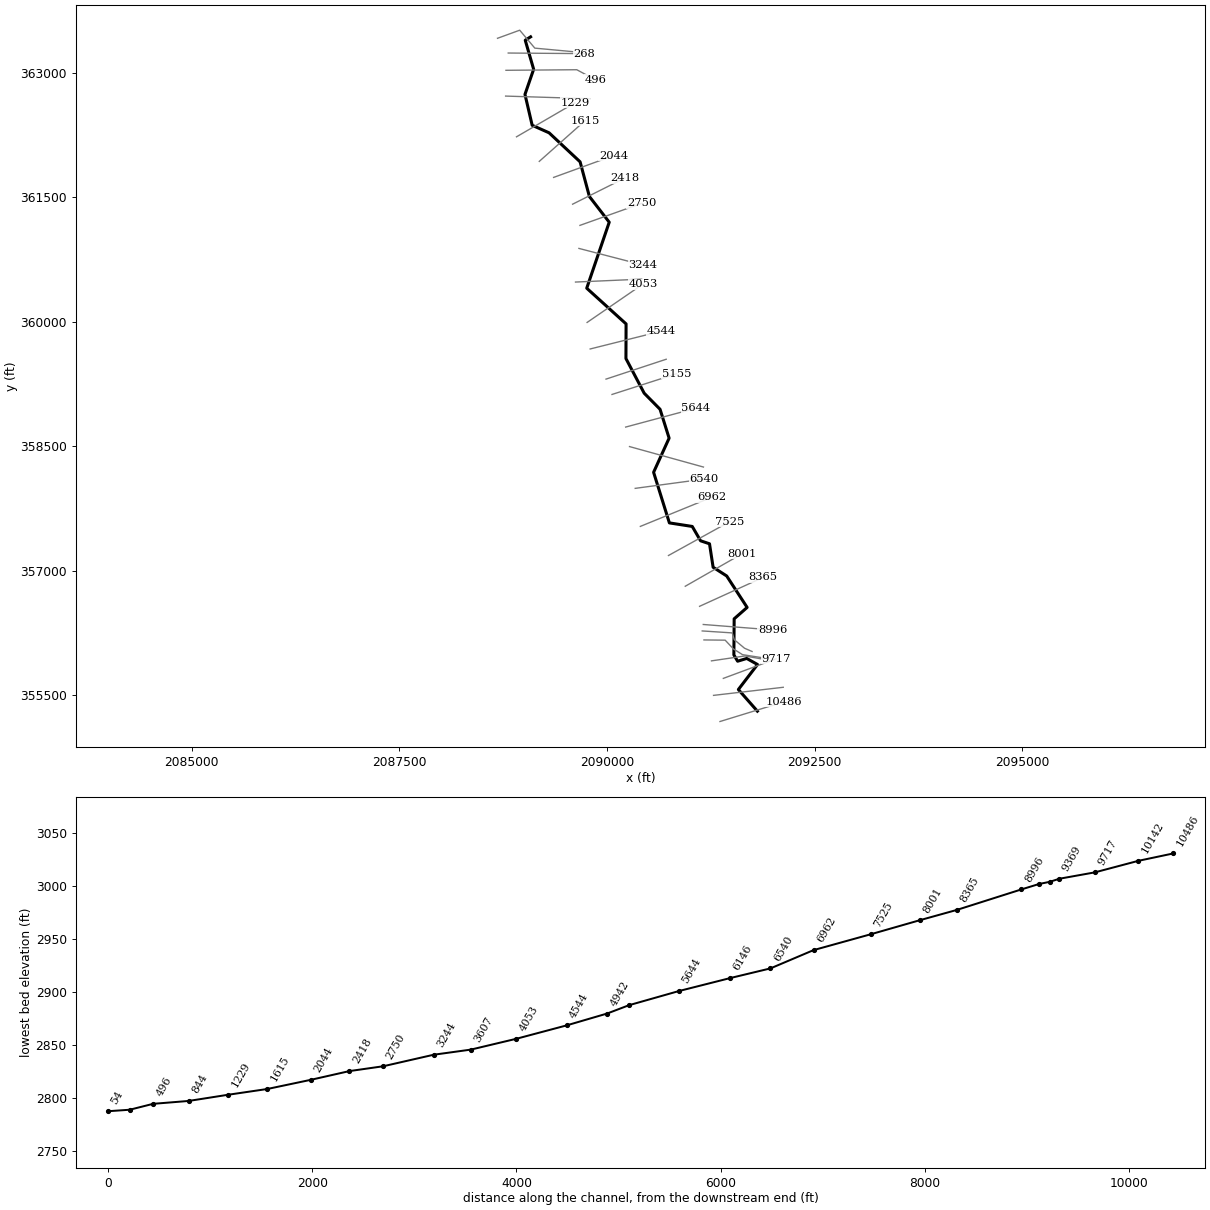
--- LAURELCK3.prj (project) ---

Proj Title=LAURELCK3
Current Plan=p01
Default Exp/Contr=0,0
English Units
Geom File=g01
Flow File=f01
Plan File=p01
BEGIN DESCRIPTION:
Stream Name- Laurel Creek 3
Flood Zone: Zone A
Greenbrier County, WV
County-Wide Study
WVDHSEM-2018-3, Flood Risk Project
HEC-RAS Version: 5.0.7
General Notes:
For the Hydrology regression was used.
END DESCRIPTION:
DSS Export Rating Curves= 0
DSS Export Rating Curve Sorted= 0
DSS Export Volume Flow Curves= 0
DXF OffsetX= 0
DXF OffsetY= 0
DXF ScaleX= 0
DXF ScaleY= 0

--- LAURELCK3.p01 (plan) ---

Plan Title=Floodplain
Program Version=5.07
Short Identifier=Floodplain
Geom File=g01
Flow File=f01
Subcritical Flow
K Sum by GR= 0
Std Step Tol= 0.01
Critical Tol= 0.01
Num of Std Step Trials= 20
Max Error Tol= 0.3
Flow Tol Ratio= 0.001
Split Flow NTrial= 30
Split Flow Tol= 0.02
Split Flow Ratio= 0.02
Log Output Level= 0
Friction Slope Method= 1
Unsteady Friction Slope Method= 2
Unsteady Bridges Friction Slope Method= 1
Parabolic Critical Depth
Global Vel Dist= 0 , 0 , 0
Global Log Level= 0
CheckData=True
Encroach Param=-1 ,0,0, 0
Mapping Interval=1HOUR
Computation Time Step Use Courant=        0
Computation Time Step Use Time Series=    0
Computation Time Step Count To Double=0
Computation Time Step Max Doubling=0
Computation Time Step Max Halving=0
Computation Time Step Residence Courant=0
Run HTab= 0
Run UNet= 0
Run Sediment= 0
Run PostProcess= 0
Run WQNet= 0
Run RASMapper= 0
UNET Theta= 0
UNET Theta Warmup= 0
UNET ZTol= 0
UNET ZSATol= 0
UNET MxIter= 0
UNET Max Iter WO Improvement= 0
UNET MaxInSteps= 0
UNET DtIC= 0
UNET DtMin= 0
UNET MaxCRTS= 0
UNET WFStab= 0
UNET SFStab= 0
UNET WFX= 1
UNET SFX= 1
UNET 1D Methodology=Finite Difference
UNET DSS MLevel= 1
UNET Pardiso=0
UNET DZMax Abort= 0
UNET Use Existing IB Tables= 0
UNET Froude Reduction=False
UNET Froude Limit= 0
UNET Froude Power= 0
UNET D1 Cores= 0
UNET D2 Coriolis=0
UNET D2 Cores= 0
UNET D2 Theta= 1
UNET D2 Theta Warmup= 1
UNET D2 Z Tol= 0.01
UNET D2 Volume Tol= 0.01
UNET D2 Max Iterations= 20
UNET D2 Equation= 0
UNET D2 RampUpFraction=0.1
UNET D2 TimeSlices= 1
UNET D2 BCVolumeCheck=0
UNET D1D2 MaxIter= 0
UNET D1D2 ZTol=0.01
UNET D1D2 QTol=0.1
UNET D1D2 MinQTol=1
Write IC File= 0
Write IC File at Fixed DateTime=0
Write IC File at Sim End=0
Echo Input=False
Echo Parameters=False
Echo Output=False
Write Detailed= 0
HDF Write Warmup=0
HDF Write Time Slices=0
HDF Flush=0
HDF Face Node Velocities=0
HDF Compression= 1
HDF Chunk Size= 1
HDF Spatial Parts= 1
HDF Use Max Rows=0
HDF Fixed Rows= 1
Calibration Method= 0
Calibration Iterations= 20
Calibration Max Change=0.05
Calibration Tolerance=0.2
Calibration Maximum=1.5
Calibration Minimum=0.5
Calibration Optimization Method= 1
WQ AD Non Conservative
WQ ULTIMATE=-1
WQ Max Comp Step=1HOUR
WQ Output Interval=15MIN
WQ Output Selected Increments= 0
WQ Output face flow=0
WQ Output face velocity=0
WQ Output face area=0
WQ Output face dispersion=0
WQ Output cell volume=0
WQ Output cell surface area=0
WQ Output cell continuity=0
WQ Output cumulative cell continuity=0
WQ Output face conc=0
WQ Output face dconc_dx=0
WQ Output face courant=0
WQ Output face peclet=0
WQ Output face adv mass=0
WQ Output face disp mass=0
WQ Output cell mass=0
WQ Output cell source sink temp=0
WQ Output nsm pathways=0
WQ Output nsm derived pathways=0
WQ Output MaxMinRange=-1
WQ Daily Max Min Mean=-1
WQ Daily Range=0
WQ Daily Time=0
WQ Create Restart=0
WQ Fixed Restart=0
WQ System Summary=0
WQ Write To DSS=0
WQ Use Fixed Temperature=0
Sorting and Armoring Iterations= 10
XS Update Threshold= 0.02
Bed Roughness Predictor= 0
Hydraulics Update Threshold= 0.02
Energy Slope Method= 1
Volume Change Method= 1
Sediment Retention Method= 0
XS Weighting Method= 0
Number of US Weighted Cross Sections= 1
Number of DS Weighted Cross Sections= 1
Upstream XS Weight=0
Main XS Weight=1
Downstream XS Weight=0
Number of DS XS's Weighted with US Boundary= 1
Upstream Boundary Weight= 1
Weight of XSs Associated with US Boundary= 0
Number of US XS's Weighted with DS Boundary= 1
Downstream Boundary Weight= 0.5
Weight of XSs Associated with DS Boundary= 0.5
Percentile Method= 0
Sediment Output Level= 3
Mass or Volume Output= 0
Output Increment Type= 1
Profile and TS Output Increment= 1
XS Output Flag= 0
XS Output Increment= 10
Write Gradation File= 0
Read Gradation Hotstart= 0
Write HDF5 File= 1
Write Binary Output= 1
Write DSS Sediment File= 0
SV Curve= 0
Specific Gage Flag= 0

--- LAURELCK3.f01 (steady flow) ---

Flow Title=H3b_combinedFlows
Program Version=5.07
Number of Profiles= 6
Profile Names=f1p,f10p,f4p,f2p,f02p,f1pplus
River Rch & RM=LAURELCK3,Main            ,10486
     442     231     309     373     620     653
River Rch & RM=LAURELCK3,Main            ,10142
     546     288     383     462     764     808
River Rch & RM=LAURELCK3,Main            ,6962
     650     345     458     551     905     961
River Rch & RM=LAURELCK3,Main            ,6540
     790     423     559     671    1100    1170
River Rch & RM=LAURELCK3,Main            ,5644
     887     477     629     754    1230    1310
River Rch & RM=LAURELCK3,Main            ,1229
    1060     573     754     902    1460    1570
Boundary for River Rch & Prof#=LAURELCK3,Main            , 1
Up Type= 0
Dn Type= 3
Dn Slope=0.01671
Boundary for River Rch & Prof#=LAURELCK3,Main            , 2
Up Type= 0
Dn Type= 3
Dn Slope=0.01671
Boundary for River Rch & Prof#=LAURELCK3,Main            , 3
Up Type= 0
Dn Type= 3
Dn Slope=0.01671
Boundary for River Rch & Prof#=LAURELCK3,Main            , 4
Up Type= 0
Dn Type= 3
Dn Slope=0.01671
Boundary for River Rch & Prof#=LAURELCK3,Main            , 5
Up Type= 0
Dn Type= 3
Dn Slope=0.01671
Boundary for River Rch & Prof#=LAURELCK3,Main            , 6
Up Type= 0
Dn Type= 3
Dn Slope=0.01671
DSS Import GetInterval= 0
DSS Import GetPeak= 0
DSS Import FillOption= 0

--- LAURELCK3.g01 (geometry) ---

Geom Title=Geometry
Program Version=5.07

River Reach=LAURELCK3       ,Main
Reach XY= 30
2091811.35900001355309.376000017     2091582.061      355570.022
2091812.72500004355871.3170000022091682.85800003355944.182999998
2091572.93600003355910.8710000072091527.96900003355987.118000001
2091531.54900001356421.4760000112091687.68200003356558.635000005
2091441.52900003356937.4810000062091278.05000003357042.378000006
2091234.62300001357325.001000017     2091126.925357361.171000004
     2091026.767 357533.826000022090751.46900003357576.518999994
2090561.23800002358185.9230000082090748.11700003358597.143999994
2090639.05800001358944.8620000032090447.90800001359138.571999997
2090228.22399999359555.8290000112090229.88000001 359973.04900001
2089756.04799999360402.986000001     2090027.006361197.653000012
2089788.42200001361506.7090000212089676.17099999361924.699000016
2089302.48700003362274.4060000182089099.03899999      362364.956
2089012.27300002362736.8540000022089116.84300004363039.532000005
     2089015.531 363389.049000012089079.95487778363429.911918506

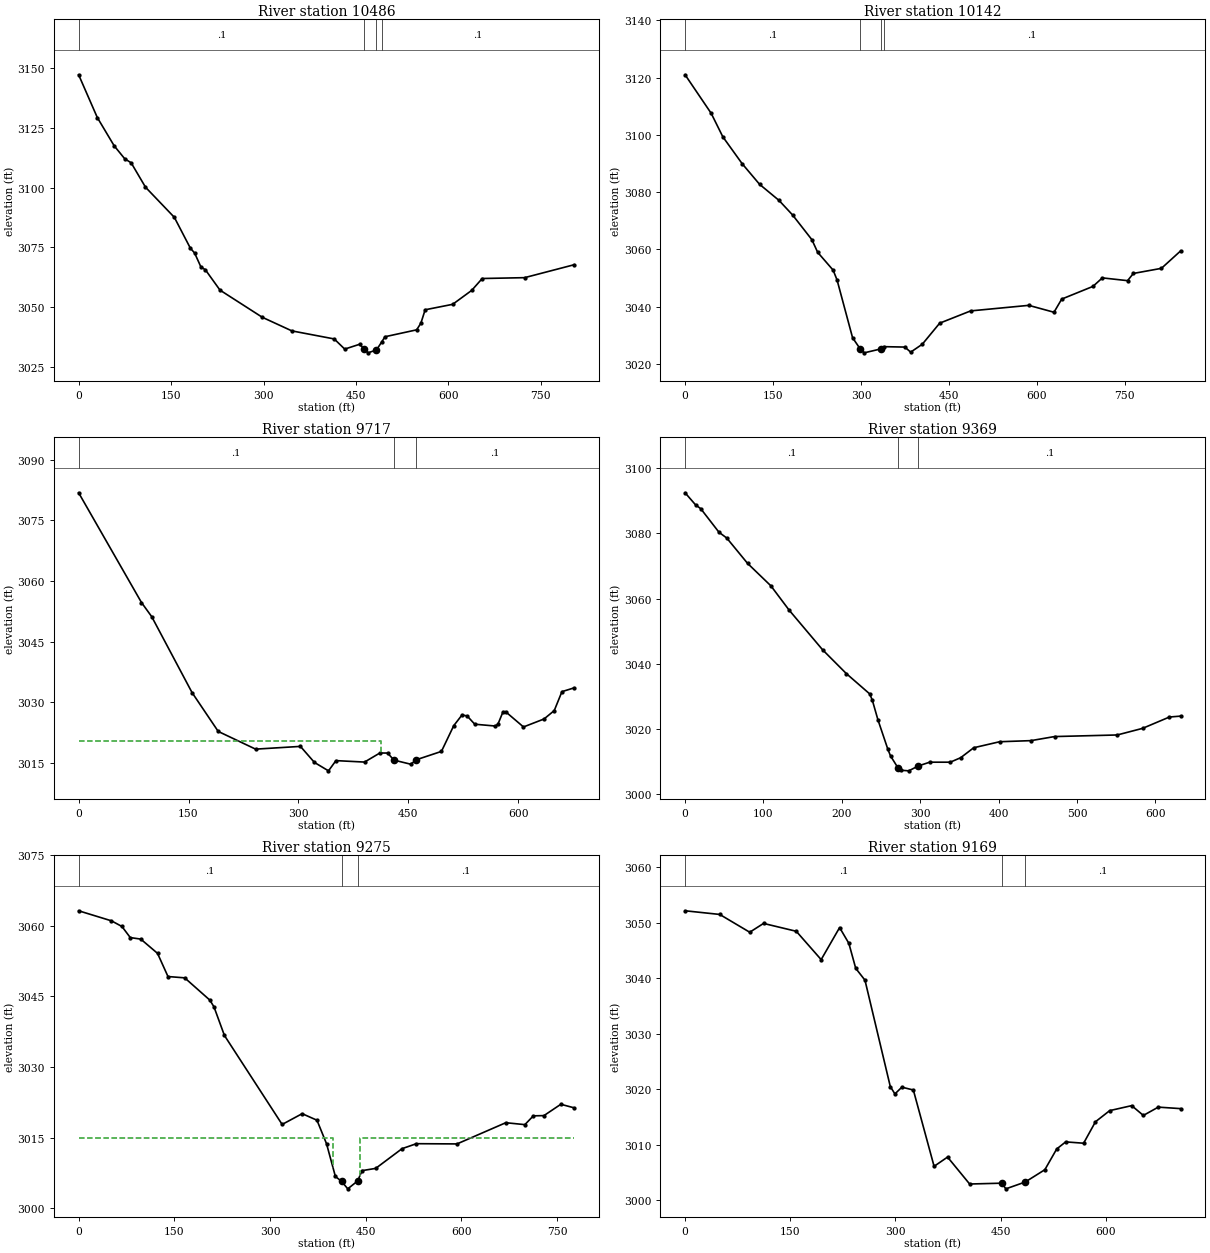
Type RM Length L Ch R = 1 ,10486   ,343.6,343.6,343.6
XS GIS Cut Line= 2
2091360.81606045355184.7601521982092129.49901002355420.854084232
#Sta/Elev= 30
       0  3147.3    30.3  3129.4    57.7 3117.55    74.9 3112.11    85.2 3110.46
   108.5 3100.24   155.3 3087.62   181.3 3074.71   188.2 3072.68   198.5  3066.8
   205.6 3065.69   229.4 3057.14     298 3045.78     346 3040.08   414.7 3036.71
   431.8 3032.46   455.9 3034.47   463.5 3032.45   469.6 3030.89   483.3 3032.11
   491.8 3035.44   497.1 3037.63   548.5 3040.52   555.4 3043.33   562.3 3048.92
   606.9  3051.2   637.8 3057.03   654.9 3062.01   723.6 3062.36   804.1 3067.78
#Mann= 4 ,-1 , 0
       0      .1       0   463.5    .045       0   483.3    .045       0
   491.8      .1       0
Bank Sta=463.5,483.3
XS Rating Curve= 0 ,0
Exp/Cntr=0.3,0.1

Type RM Length L Ch R = 1 ,10142   ,425.2,425.2,425.2
XS GIS Cut Line= 2
     2091283.261      355499.617     2092122.754      355596.949
#Sta/Elev= 30
       0 3120.97    44.5 3107.51    64.3 3099.33    97.3 3089.93     127 3082.73
   160.1 3077.12   183.2 3072.05   216.2  3063.4   226.1 3058.98   252.5 3052.75
   259.2  3049.3   285.6 3029.17   298.8 3025.21   305.4 3023.89  333.48 3025.24
   338.4 3026.05   374.8  3025.9   384.7 3024.13   404.5 3026.89   434.2 3034.25
     487 3038.53   586.1 3040.47   629.1 3038.06   642.3 3042.66   695.5 3047.08
   711.6 3050.06   754.6 3049.09   764.5 3051.61   812.3 3053.39   845.1 3059.48
#Mann= 4 ,-1 , 0
       0      .1       0   298.8    .045       0  333.48    .045       0
   338.4      .1       0
Bank Sta=298.8,333.48
XS Rating Curve= 0 ,0
Exp/Cntr=0.3,0.1

Type RM Length L Ch R = 1 ,9717    ,347.6,347.6,347.6
XS GIS Cut Line= 2
 2091401.1943058355704.2199598192092035.41576791355939.694163733
#Sta/Elev= 30
       0 3081.84    85.8 3054.68    99.8 3051.17   154.8  3032.4   190.6 3022.77
   241.6 3018.39   302.8 3019.07   321.9  3015.1   341.1 3013.02   351.3 3015.55
   390.3 3015.19   411.3 3017.44   421.8 3017.42   430.5 3015.67   453.4 3014.66
   461.1 3015.77   495.3 3017.83   512.1  3024.2   523.3 3026.83   530.3 3026.62
   540.8 3024.56   568.8 3024.11   572.3 3024.51   579.3 3027.61   582.8 3027.67
   607.3 3023.88   635.3 3025.85   649.3 3027.93   659.8 3032.62   676.5 3033.56
#Mann= 3 , 0 , 0
       0      .1       0   430.5    .045       0   461.1      .1       0
#XS Ineff= 2 , 0
          413.28 3020.37
Permanent Ineff=
       F       F
Bank Sta=430.5,461.1
XS Rating Curve= 0 ,0
Exp/Cntr=0.3,0.1

Type RM Length L Ch R = 1 ,9369    ,94.1,94.1,94.1
XS GIS Cut Line= 3
2091258.43294175355915.080135449  2091661.282538 355974.15380333
2091882.80879255355934.771358076
#Sta/Elev= 30
       0 3092.52    13.4 3088.79      20 3087.62    43.2 3080.39    53.2 3078.59
    79.7 3070.81   109.5 3063.89   132.7 3056.44   175.4 3044.24   205.7 3036.92
   235.5 3030.67   238.9  3028.7     246 3022.72   258.7 3013.63   262.1 3011.59
   271.6 3007.92   275.3  3007.2   285.3 3007.01   297.6 3008.52   312.1 3009.67
   338.3 3009.67   351.6 3011.05   368.2 3014.11   401.3 3015.96   441.3  3016.3
   471.3 3017.55   551.3 3018.04   583.6 3020.07   617.9 3023.56   632.2 3023.84
#Mann= 3 , 0 , 0
       0      .1       0   271.6    .045       0   297.6      .1       0
Bank Sta=271.6,297.6
XS Rating Curve= 0 ,0
Exp/Cntr=0.5,0.3

Type RM Length L Ch R = 1 ,9275    ,106.2,106.2,106.2
XS GIS Cut Line= 5
2091167.70348875356167.0897688912091423.36580333356164.310830689
  2091522.623512356058.6619671042091632.56617167 355989.74268791
2091876.24505167355952.001177875
#Sta/Elev= 30
       0 3063.22    51.5 3061.08    67.9 3059.88      81 3057.52    97.4  3057.2
   123.7 3054.17   140.1 3049.24   166.3 3048.96   205.7 3044.23   212.2  3042.8
   228.6 3036.71   319.1 3017.79   350.5 3020.08   373.7 3018.69   388.7 3013.69
   402.6 3006.73   412.3 3005.69     422  3004.1   437.5 3005.78   444.4 3007.97
   465.8 3008.45   507.1 3012.64   529.6  3013.7   593.3 3013.65   669.8 3018.16
   699.7 3017.75     713 3019.62   729.6 3019.67   756.1 3022.08     777 3021.32
#Mann= 3 , 0 , 0
       0      .1       0   412.3    .045       0   437.5      .1       0
#XS Ineff= 2 , 0
          399.11    3015  441.03            3015
Permanent Ineff=
       F       F
Bank Sta=412.3,437.5
XS Rating Curve= 0 ,0
Exp/Cntr=0.5,0.3

Type RM Length L Ch R = 1 ,9169    ,172.5,172.5,172.5
XS GIS Cut Line= 5
2091146.86145223 356275.468358772091508.12341849356251.847384053
2091533.13386231356169.868707093 2091656.7966123356067.047993618
2091747.11210387 356028.14285879
#Sta/Elev= 30
       0 3052.17    49.4 3051.51    92.2  3048.3   111.9 3049.89   158.6 3048.47
   194.1 3043.36   220.4 3049.14   233.6  3046.3   243.4 3041.79   256.6 3039.65
   292.7 3020.47   299.3 3019.13   309.2 3020.35   325.6 3019.84   355.2 3006.07
   374.4 3007.74   405.9 3002.88   451.7 3003.03   457.6 3002.01   485.2 3003.24
   513.2 3005.46   530.1  3009.2   542.9 3010.48   568.5 3010.24   585.4 3014.11
   605.7 3016.12   637.1 3017.02   653.7 3015.25     675 3016.75   706.9 3016.48
#Mann= 3 , 0 , 0
       0      .1       0   451.7    .045       0   485.2      .1       0
Bank Sta=451.7,485.2
XS Rating Curve= 0 ,0
Exp/Cntr=0.5,0.3

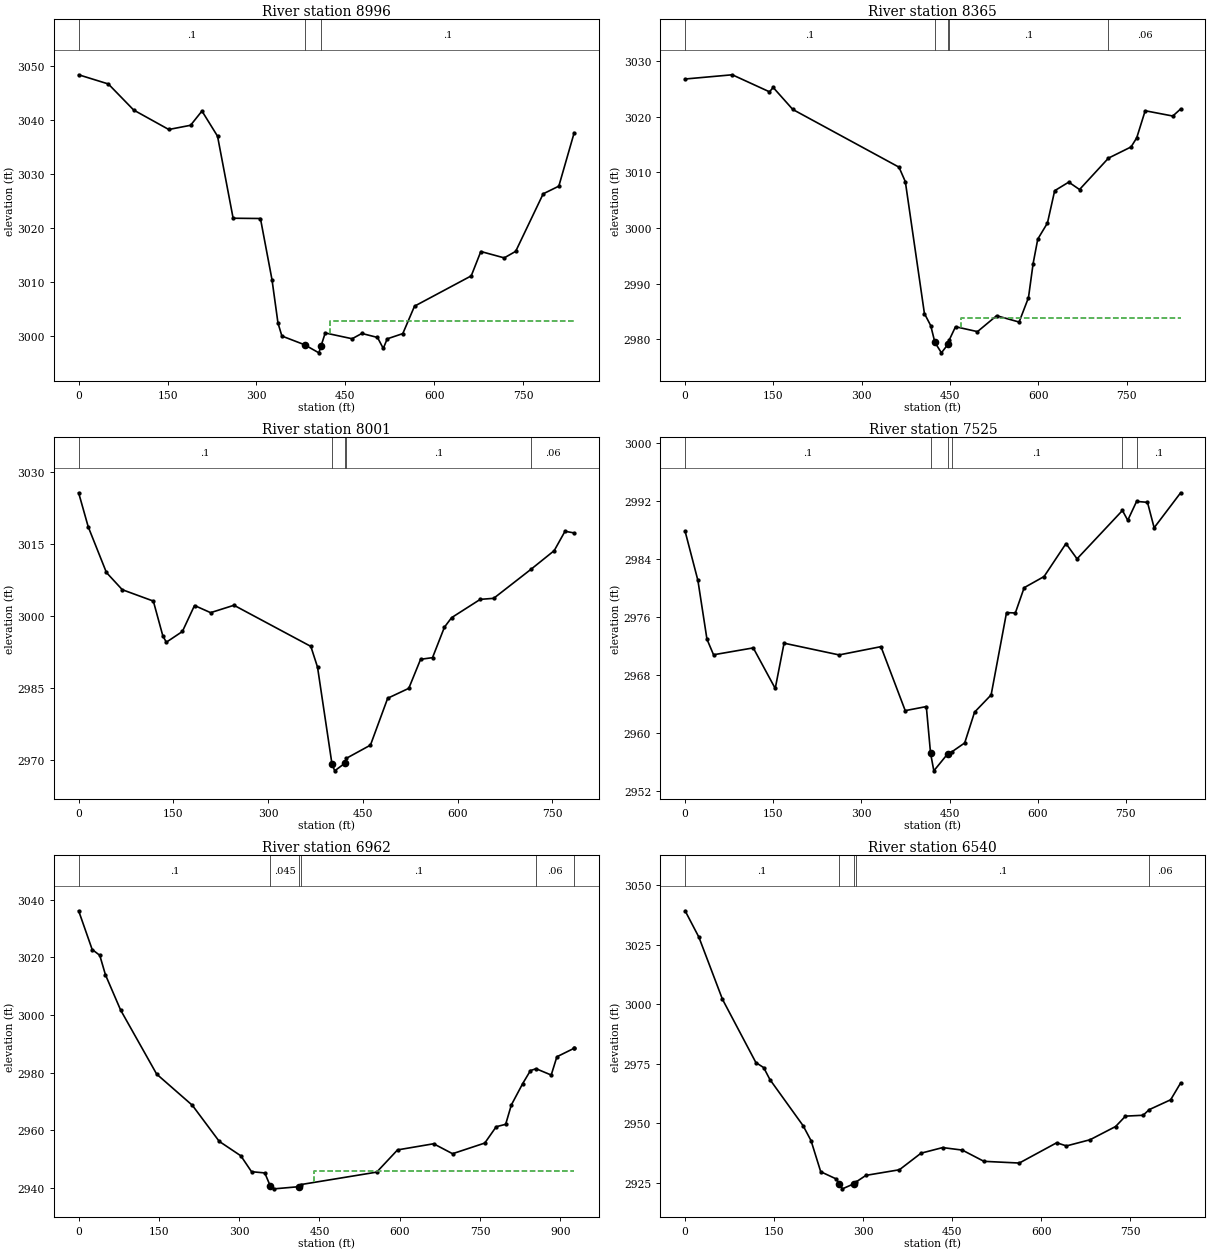
Type RM Length L Ch R = 1 ,8996    ,631.3,631.3,631.3
XS GIS Cut Line= 2
2091159.36667414356353.2786284272091993.04813475356287.973580679
#Sta/Elev= 30
       0 3048.39    50.1 3046.69    92.9 3041.86   152.1 3038.26   188.9 3039.04
   208.1 3041.68   234.4 3037.02   260.7 3021.83   306.8 3021.78   326.3 3010.45
   336.4 3002.42     343 3000.02   381.2 2998.41   405.4 2996.91     409 2998.16
   416.1 3000.59   461.5 2999.52   477.9  3000.5   504.3 2999.76   514.1 2997.72
   520.7  2999.5     547 3000.47   566.8 3005.55   662.5 3011.16   678.7 3015.67
   718.2 3014.49   737.5  3015.7   783.9 3026.35   810.3 3027.77   836.2 3037.65
#Mann= 3 , 0 , 0
       0      .1       0   381.2    .045       0     409      .1       0
#XS Ineff= 2 , 0
                          423.62         3002.82
Permanent Ineff=
       F       F
Bank Sta=381.2,409
XS Rating Curve= 0 ,0
Exp/Cntr=0.3,0.1

Type RM Length L Ch R = 1 ,8365    ,364.4,364.4,364.4
XS GIS Cut Line= 2
2091115.02238595356572.0671821062091880.89582155356920.697220586
#Sta/Elev= 30
       0 3026.77    80.1 3027.53   143.3 3024.47   149.6 3025.25   182.9  3021.3
   363.2 3010.94     374 3008.33   406.4 2984.65   417.1 2982.48   424.2 2979.46
   435.3 2977.59  447.23 2979.25   448.5 2979.88   459.2 2982.28   496.5  2981.4
     529 2984.26   567.2 2983.12   583.1  2987.5     591 2993.63   598.9 2998.02
   615.3  3000.9   627.6 3006.71   651.5 3008.25   669.8 3006.92  718.963012.564
   757.3 3014.57   766.9  3016.2   781.3 3021.07   828.2 3020.12   841.5 3021.39
#Mann= 5 ,-1 , 0
       0      .1       0   424.2    .045       0  447.23    .045       0
   448.5      .1       0  718.96     .06       0
#XS Ineff= 2 , 0
                           467.9         2983.87
Permanent Ineff=
       F       F
Bank Sta=424.2,447.23
XS Rating Curve= 0 ,0
Exp/Cntr=0.3,0.1

Type RM Length L Ch R = 1 ,8001    ,475.2,475.2,475.2
XS GIS Cut Line= 2
     2090942.597      356813.607     2091623.925      357202.937
#Sta/Elev= 30
       0  3025.7    15.2 3018.61      44 3009.11    69.1 3005.53   118.3 3003.16
   133.4 2995.89   138.9  2994.6   164.3 2996.83   183.5 3002.24     209 3000.75
     246 3002.29   367.7 2993.73   378.3 2989.41  401.13 2969.29   405.5 2967.83
  422.17 2969.47     424 2970.44   462.1 2973.18   489.4 2982.94   522.8    2985
   541.5 2991.04   560.4 2991.39   579.3 2997.74   590.6 2999.71     636 3003.52
   657.2 3003.73  717.063009.852   753.1 3013.66   770.2 3017.69   784.7 3017.34
#Mann= 5 ,-1 , 0
       0      .1       0  401.13    .045       0  422.17    .045       0
     424      .1       0  717.06     .06       0
Bank Sta=401.13,422.17
XS Rating Curve= 0 ,0
Exp/Cntr=0.3,0.1

Type RM Length L Ch R = 1 ,7525    ,563.4,563.4,563.4
XS GIS Cut Line= 2
2090740.43053609357184.0241645452091478.48774521357591.995486171
#Sta/Elev= 30
       0 2987.79    21.8    2981    37.2 2972.89    48.4 2970.74     116 2971.69
   153.4 2966.09   168.4 2972.34   262.1 2970.72   333.3 2971.86   374.6 2963.03
   410.5 2963.59   417.7 2957.17   423.3 2954.72   446.7 2957.05   453.9 2957.34
   475.8 2958.57   492.6 2962.82   520.8  2965.2     547 2976.56     562 2976.51
     577    2980   610.9 2981.54   648.2 2986.09     667 2983.98  744.242990.655
   753.3  2989.3  768.36 2991.91   786.9 2991.78   798.2 2988.27   843.3  2993.1
#Mann= 6 ,-1 , 0
       0      .1       0   417.7    .045       0   446.7    .045       0
   453.9      .1       0  744.24     .06       0  768.36      .1       0
Bank Sta=417.7,446.7
XS Rating Curve= 0 ,0
Exp/Cntr=0.3,0.1

Type RM Length L Ch R = 1 ,6962    ,421.8,421.8,421.8
XS GIS Cut Line= 2
2090401.75234003 357534.46601903     2091258.928      357884.265
#Sta/Elev= 30
       0 3036.16    25.3 3022.72    39.5  3020.7    50.1 3013.94    78.5 3001.69
   145.8 2979.48   212.5 2968.65   262.7 2956.14   303.1 2951.12     323 2945.62
   347.8 2945.19   358.3 2940.53   365.5 2939.67   411.6 2940.42   415.1 2941.15
   556.9 2945.47   595.8 2953.18   663.2 2955.31   698.6 2951.86   758.8 2955.56
   780.1 2961.22   797.8 2962.06   808.4 2968.77   829.7 2976.22   844.1  2980.7
  854.52 2981.36   882.9 2979.16   893.5  2985.5  925.032988.388   925.8 2988.46
#Mann= 6 ,-1 , 0
       0      .1       0   358.3    .045       0   411.6    .045       0
   415.1      .1       0  854.52     .06       0  925.03      .1       0
#XS Ineff= 2 , 0
                           440.3         2945.98
Permanent Ineff=
       F       F
Bank Sta=358.3,411.6
XS Rating Curve= 0 ,0
Exp/Cntr=0.3,0.1

Type RM Length L Ch R = 1 ,6540    ,394.1,394.1,394.1
XS GIS Cut Line= 2
2090339.87687486357992.549147404 2091166.9460087358103.814053302
#Sta/Elev= 30
       0 3039.18    23.2 3028.12    62.9 3002.03   119.2 2975.45   132.4 2973.32
   142.8 2968.33   198.7 2948.95   212.1 2942.66   228.4 2929.61   254.9 2926.54
  259.19 2924.56   264.9 2922.43   284.7  2924.6   287.8  2925.3   304.6 2928.09
   360.9 2930.44   397.3  2937.4   433.7 2939.75   466.8  2938.7   503.2 2933.98
   562.8 2933.26   625.7 2941.77   642.2 2940.45     682 2943.05     725  2948.6
   741.6 2952.96   771.3 2953.32  781.612955.687   817.7 2959.83   834.5 2966.88
#Mann= 5 ,-1 , 0
       0      .1       0  259.19    .045       0   284.7    .045       0
   287.8      .1       0  781.61     .06       0
Bank Sta=259.19,284.7
XS Rating Curve= 0 ,0
Exp/Cntr=0.3,0.1

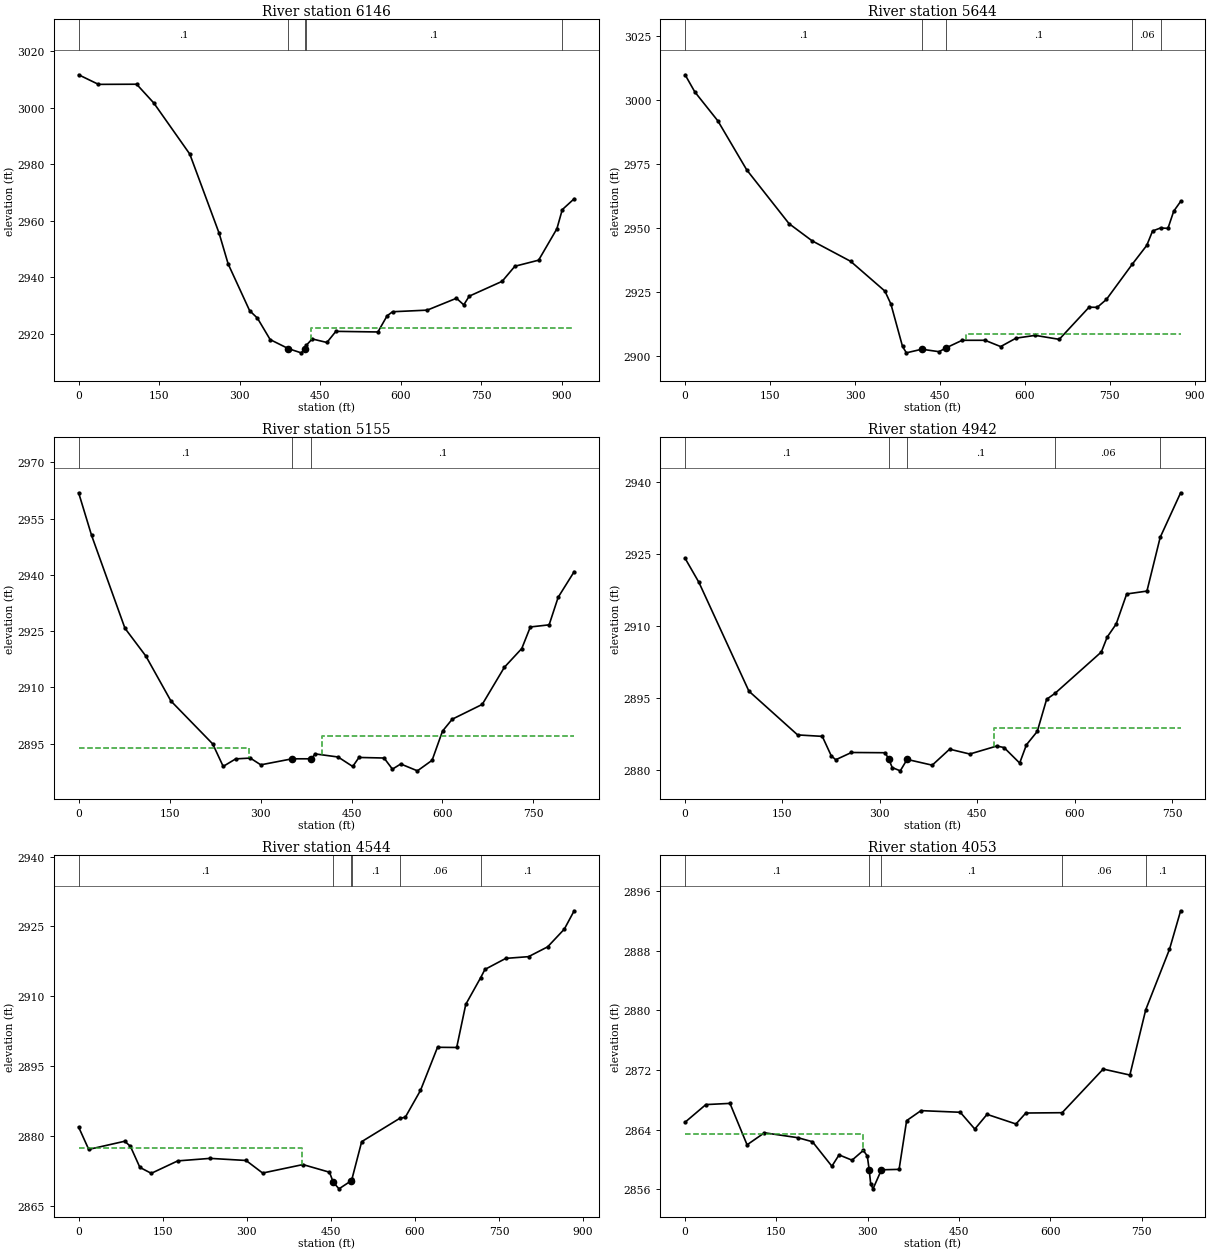
Type RM Length L Ch R = 1 ,6146    ,502.5,502.5,502.5
XS GIS Cut Line= 2
2090271.45215182358495.664942909     2091161.595      358249.262
#Sta/Elev= 30
       0 3011.63      37 3008.24   108.1 3008.29   140.1 3001.65   207.2 2983.58
   261.7 2955.68   278.7 2944.73   318.7 2928.23   333.2 2925.59     357 2917.99
  391.03 2914.79   414.7 2913.31  422.54 2914.79   424.1 2915.92   435.3 2918.23
   462.7 2916.97   479.5 2920.91   557.8 2920.69   574.9 2926.39   585.1 2927.84
   649.7 2928.41   704.2 2932.61   717.8 2930.27     728 2933.35   789.3 2938.59
   813.1 2943.93   857.3 2946.07   891.4 2957.18  901.442963.947   923.6 2967.79
#Mann= 5 ,-1 , 0
       0      .1       0  391.03    .045       0  422.54    .045       0
   424.1      .1       0  901.44     .06       0
#XS Ineff= 2 , 0
                          433.95         2922.07
Permanent Ineff=
       F       F
Bank Sta=391.03,422.54
XS Rating Curve= 0 ,0
Exp/Cntr=0.3,0.1

Type RM Length L Ch R = 1 ,5644    ,488.2,488.2,488.2
XS GIS Cut Line= 2
2090224.90313876358730.6063565282091070.21715148358957.376946968
#Sta/Elev= 30
       0 3009.92    17.2  3003.2    57.9 2991.86   108.9 2972.67   183.6 2951.63
   224.4  2944.9   292.3  2936.9   352.9 2925.23   363.5 2920.15     384 2903.56
   390.8 2901.06     418 2902.47   448.6 2901.51     460 2902.91   489.3 2905.97
   529.7 2905.97   557.3 2903.51   584.4  2906.8   618.4  2907.9   660.8 2906.34
   713.5 2918.93   727.9 2918.87   744.1 2921.96  789.642935.723   815.4 2943.13
   825.6 2948.75  839.822949.961   852.8 2949.79     863 2956.52   875.2 2960.33
#Mann= 5 ,-1 , 0
       0      .1       0     418    .045       0     460      .1       0
  789.64     .06       0  839.82      .1       0
#XS Ineff= 2 , 0
                          496.78         2908.36
Permanent Ineff=
       F       F
Bank Sta=418,460
XS Rating Curve= 0 ,0
Exp/Cntr=0.3,0.1

Type RM Length L Ch R = 1 ,5155    ,213.4,213.4,213.4
XS GIS Cut Line= 2
2090060.46124801359123.3418306772090838.56129845359373.069887407
#Sta/Elev= 30
       0 2961.88    21.3 2950.54    76.4 2925.74   110.9 2918.32   152.2 2906.35
   221.1  2894.9   238.4  2888.9     259 2890.91   283.1 2891.12   300.4 2889.32
   352.1 2890.93   383.9 2890.93     390 2892.24   427.9 2891.41     452 2888.88
   462.3 2891.29   503.7 2891.14   517.5 2888.17   531.2 2889.55   558.7 2887.72
   582.9 2890.53   600.1 2898.32   616.1 2901.49   665.6 2905.44   702.1 2915.34
   730.8 2920.34   744.9 2926.09   775.9 2926.66   790.8 2934.01   817.2 2940.84
#Mann= 3 , 0 , 0
       0      .1       0   352.1    .045       0   383.9      .1       0
#XS Ineff= 2 , 0
           281.6 2893.93  401.48         2897.02
Permanent Ineff=
       F       F
Bank Sta=352.1,383.9
XS Rating Curve= 0 ,0
Exp/Cntr=0.3,0.1

Type RM Length L Ch R = 1 ,4942    ,398.2,398.2,398.2
XS GIS Cut Line= 2
2089988.32581648359308.1709624292090713.05077948359547.380880284
#Sta/Elev= 30
       0 2924.13    21.3 2919.12    98.3 2896.47   173.3 2887.36   211.3 2887.06
   225.1 2883.01     232 2882.19   256.2  2883.7     308 2883.65   313.5 2882.38
     319 2880.56   331.4 2879.88   341.9 2882.26   380.6 2881.06   407.4 2884.39
   438.5 2883.38   480.1 2885.05   491.2 2884.73   515.3  2881.5   525.7  2885.3
   542.4 2888.09   556.8 2894.78  569.622896.005   641.1 2904.63   650.1 2907.74
   663.9 2910.44   680.1 2916.71   711.3 2917.31   731.72928.497   763.2 2937.78
#Mann= 5 ,-1 , 0
       0      .1       0   313.5    .045       0   341.9      .1       0
  569.62     .06       0   731.7      .1       0
#XS Ineff= 2 , 0
                          475.64         2888.89
Permanent Ineff=
       F       F
Bank Sta=313.5,341.9
XS Rating Curve= 0 ,0
Exp/Cntr=0.3,0.1

Type RM Length L Ch R = 1 ,4544    ,490.6,490.6,490.6
XS GIS Cut Line= 2
2089797.50188655359671.1218258322090655.12744157359885.906962769
#Sta/Elev= 30
       0 2881.91      18 2877.12    82.3 2878.87    92.4 2877.77   109.3 2873.25
   129.6 2871.98   176.8 2874.65   234.5 2875.19   298.7 2874.74   328.3 2872.04
   400.2 2873.86   447.5 2872.22   454.3 2870.07   464.5 2868.65   486.7 2870.41
   487.8 2870.82     505 2878.78  572.672883.771   582.8 2884.02   609.9 2889.78
   640.3 2899.04   674.5    2899   690.7 2908.26  717.322913.999   724.9 2915.76
   762.1 2918.13   802.7  2918.5   836.8 2920.61   866.5 2924.41   884.1 2928.35
#Mann= 6 ,-1 , 0
       0      .1       0   454.3    .045       0   486.7    .045       0
   487.8      .1       0  572.67     .06       0  717.32      .1       0
#XS Ineff= 2 , 0
          397.79 2877.41
Permanent Ineff=
       F       F
Bank Sta=454.3,486.7
XS Rating Curve= 0 ,0
Exp/Cntr=0.3,0.1

Type RM Length L Ch R = 1 ,4053    ,446.2,446.2,446.2
XS GIS Cut Line= 2
2089760.58749278359990.673749948     2090431.601      360451.412
#Sta/Elev= 30
       0    2865    34.1 2867.36    73.7 2867.52   101.8 2861.97   130.3 2863.58
   185.4 2862.92   209.2 2862.38   241.1  2859.1   252.9 2860.62   274.2 2859.91
   292.8 2861.22   299.3 2860.47   302.4 2858.62   304.9 2856.72   308.7 2856.07
   322.5 2858.62   351.5 2858.68   363.9 2865.21   387.5 2866.55     452 2866.33
   475.9 2864.08     496 2866.05   543.5 2864.76   559.7 2866.23  619.352866.273
   686.8 2872.12   730.6 2871.32  756.722880.082   795.7 2888.17     814 2893.33
#Mann= 5 ,-1 , 0
       0      .1       0   302.4    .045       0   322.5      .1       0
  619.35     .06       0  756.72      .1       0
#XS Ineff= 2 , 0
          292.99 2863.48
Permanent Ineff=
       F       F
Bank Sta=302.4,322.5
XS Rating Curve= 0 ,0
Exp/Cntr=0.3,0.1

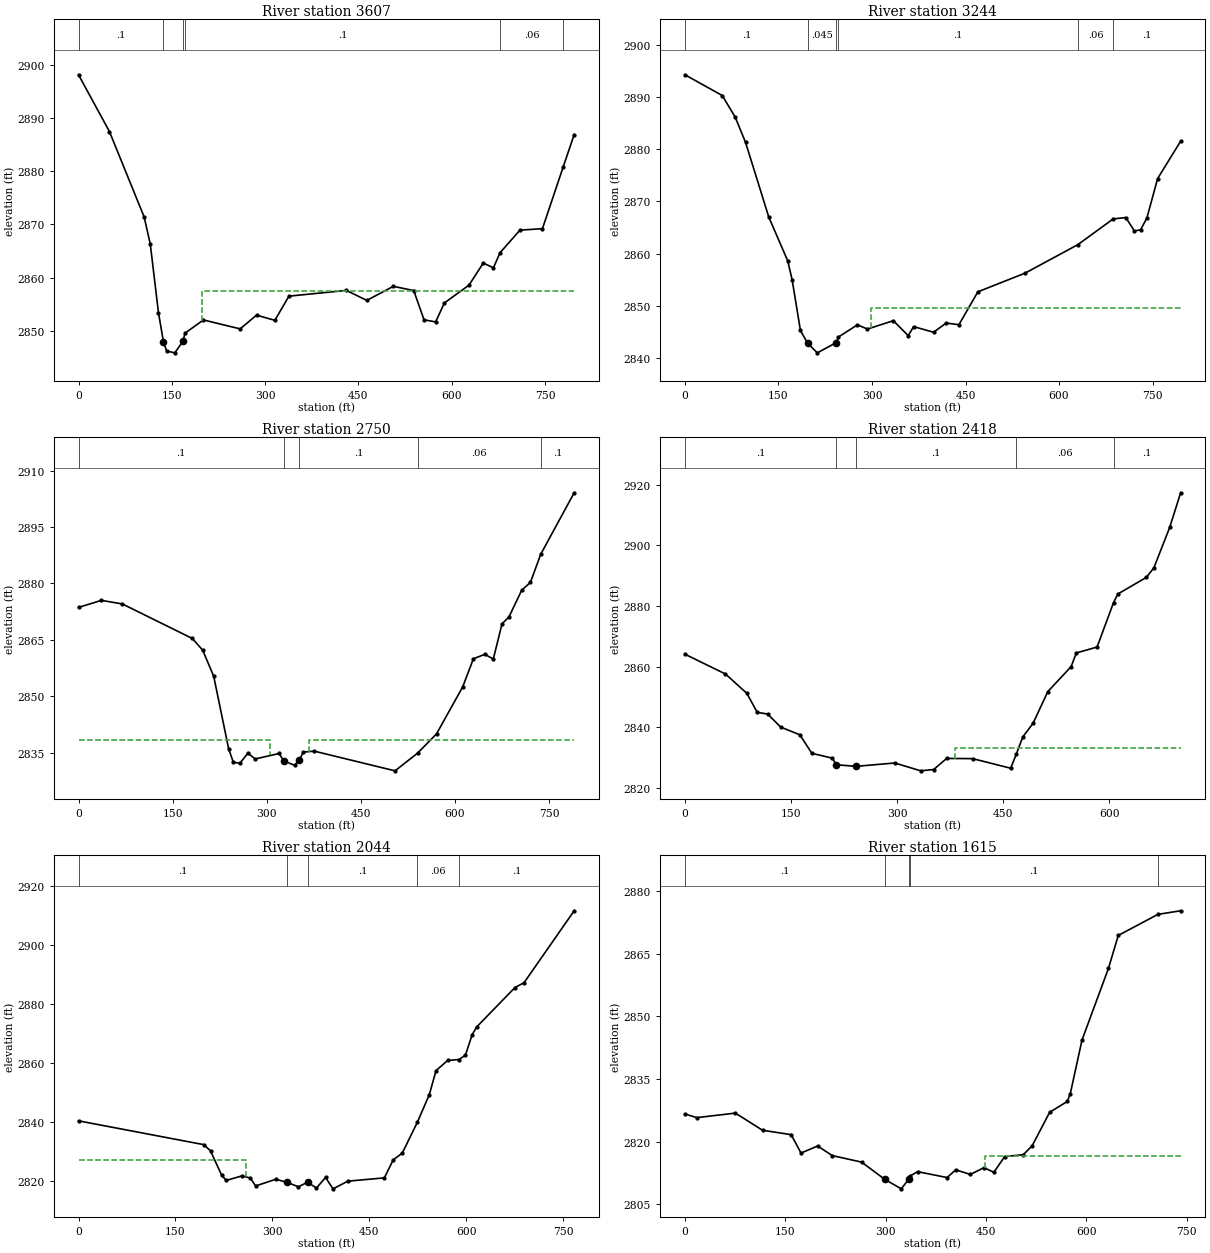
Type RM Length L Ch R = 1 ,3607    ,362.6,362.6,362.6
XS GIS Cut Line= 2
2089620.93673234 360477.014367062090417.03713404360512.062812418
#Sta/Elev= 30
       0 2898.17    49.7 2887.49   105.6 2871.38   115.4  2866.3   128.5 2853.42
   136.5 2847.95   141.7 2846.17   154.8 2845.83     168 2848.02   171.2 2849.53
   200.8 2852.02   259.9 2850.34   286.2 2852.92   315.7 2851.95   338.3  2856.5
   430.7 2857.58   463.5  2855.7   506.2 2858.35     539 2857.55   555.5 2852.04
   574.2 2851.66   588.3 2855.23   627.8 2858.57   650.7 2862.72   667.1 2861.84
  677.752864.678   709.8 2868.93   745.9  2869.2   779.22880.807   796.9 2886.91
#Mann= 6 ,-1 , 0
       0      .1       0   136.5    .045       0     168    .045       0
   171.2      .1       0  677.75     .06       0   779.2      .1       0
#XS Ineff= 2 , 0
                          198.97         2857.44
Permanent Ineff=
       F       F
Bank Sta=136.5,168
XS Rating Curve= 0 ,0
Exp/Cntr=0.3,0.1

Type RM Length L Ch R = 1 ,3244    ,494.7,494.7,494.7
XS GIS Cut Line= 2
2089661.93812478360882.030501819     2090431.601      360682.577
#Sta/Elev= 30
       0 2894.22    59.8 2890.25    80.5 2886.13    97.1 2881.31   134.4 2867.01
   164.9 2858.59     172 2854.94   185.2  2845.3   196.8 2842.84   212.3 2841.02
   242.8 2842.98   246.2 2844.05   276.7 2846.38   292.6 2845.57   334.3 2847.17
   358.1 2844.31   366.8 2846.04   398.7 2844.96   419.1 2846.72   439.4  2846.4
   469.9  2852.7   545.6 2856.27  630.342861.727   686.92866.643   707.1 2866.91
     721 2864.33   730.9 2864.57     741 2866.83   758.2 2874.37   795.1 2881.51
#Mann= 6 ,-1 , 0
       0      .1       0   196.8    .045       0   242.8    .045       0
   246.2      .1       0  630.34     .06       0   686.9      .1       0
#XS Ineff= 2 , 0
                          298.94         2849.54
Permanent Ineff=
       F       F
Bank Sta=196.8,242.8
XS Rating Curve= 0 ,0
Exp/Cntr=0.3,0.1

Type RM Length L Ch R = 1 ,2750    ,331.5,331.5,331.5
XS GIS Cut Line= 2
2089674.34388717361159.6245647452090418.70610763361424.991365312
#Sta/Elev= 30
       0  2873.6    36.5 2875.48    69.9 2874.52   181.5 2865.34   198.1 2862.19
   215.5 2855.31   239.3 2836.05   246.8 2832.43   257.3 2832.16   270.1 2834.85
   281.7  2833.3     320 2834.76   326.9  2832.8   344.4 2831.62   352.3 2833.06
   358.3 2835.12   375.7 2835.38   504.6 2830.14  540.72 2834.87   570.8 2839.98
   612.5 2852.47   629.6 2859.95   647.6 2861.12   661.3 2859.89   675.2 2869.24
   686.1 2871.03   706.6 2878.19   720.5 2880.26  736.922887.749   790.2 2904.09
#Mann= 5 ,-1 , 0
       0      .1       0   326.9    .045       0   352.3      .1       0
  540.72     .06       0  736.92      .1       0
#XS Ineff= 2 , 0
          305.83 2838.41  367.23         2838.41
Permanent Ineff=
       F       F
Bank Sta=326.9,352.3
XS Rating Curve= 0 ,0
Exp/Cntr=0.3,0.1

Type RM Length L Ch R = 1 ,2418    ,373.7,373.7,373.7
XS GIS Cut Line= 2
2089585.81859655361414.675811481     2090212.602      361728.902
#Sta/Elev= 30
       0 2864.06    57.3 2857.52    87.5 2851.16   102.2 2844.87   116.9 2844.32
   135.5 2839.99   162.4 2837.48   179.5 2831.35   208.6 2829.75   213.8 2827.59
   241.7 2827.05   296.7 2828.16   333.5 2825.57   351.8 2826.01   370.1 2829.66
   406.9  2829.6   460.7 2826.43  468.932831.235   477.8 2836.75   492.4 2841.28
   513.2 2851.71   546.2 2859.97   553.6 2864.48   582.9 2866.43  606.172881.075
   612.2 2883.92   652.7 2889.43   663.3  2892.6   685.6 2905.89   701.1 2917.34
#Mann= 5 ,-1 , 0
       0      .1       0   213.8    .045       0   241.7      .1       0
  468.93     .06       0  606.17      .1       0
#XS Ineff= 2 , 0
                          382.45         2833.25
Permanent Ineff=
       F       F
Bank Sta=213.8,241.7
XS Rating Curve= 0 ,0
Exp/Cntr=0.3,0.1

Type RM Length L Ch R = 1 ,2044    ,429.8,429.8,429.8
XS GIS Cut Line= 2
2089357.23890536361737.0894263562090078.23549558361999.118279746
#Sta/Elev= 30
       0 2840.43   193.8 2832.38   204.3 2830.28   221.7 2821.94   228.7 2820.28
   253.1 2821.81   265.9 2821.07   274.1  2818.4   305.5 2820.67     323 2819.58
   340.4 2818.12   354.4 2819.65   368.3 2817.69   382.3 2821.26   393.9 2817.42
   416.9 2820.02   473.3 2821.13     487 2827.22     501 2829.49  524.312839.903
   542.9 2849.28   553.3 2857.44   571.3 2860.87  588.74 2861.19   598.8 2862.65
   609.2 2869.57   616.2 2872.21   675.5 2885.56   689.5 2887.18   767.1 2911.53
#Mann= 5 ,-1 , 0
       0      .1       0     323    .045       0   354.4      .1       0
  524.31     .06       0  588.74      .1       0
#XS Ineff= 2 , 0
             259 2827.22
Permanent Ineff=
       F       F
Bank Sta=323,354.4
XS Rating Curve= 0 ,0
Exp/Cntr=0.3,0.1

Type RM Length L Ch R = 1 ,1615    ,386.1,386.1,386.1
XS GIS Cut Line= 2
2089184.58736249361930.194547366     2089738.106      362422.396
#Sta/Elev= 30
       0 2826.63    17.7 2825.75    75.3 2826.84   115.9 2822.73   158.7 2821.67
   173.4 2817.26   198.2 2818.96   220.1 2816.66     264 2815.09   298.6 2810.96
   323.2 2808.69   334.3 2810.96   336.1 2811.72   347.5 2812.81   391.8 2811.39
   404.5 2813.25   426.5 2812.14   446.7 2813.76   461.6 2812.66   477.8 2816.43
   505.5 2816.87   518.7 2818.98     545 2827.04   571.4 2829.63   575.8 2831.49
   593.3 2844.34   632.8  2861.5   647.5 2869.41   706.82874.465   740.7 2875.32
#Mann= 5 ,-1 , 0
       0      .1       0   298.6    .045       0   334.3    .045       0
   336.1      .1       0   706.8     .06       0
#XS Ineff= 2 , 0
                          448.41         2816.56
Permanent Ineff=
       F       F
Bank Sta=298.6,334.3
XS Rating Curve= 0 ,0
Exp/Cntr=0.3,0.1

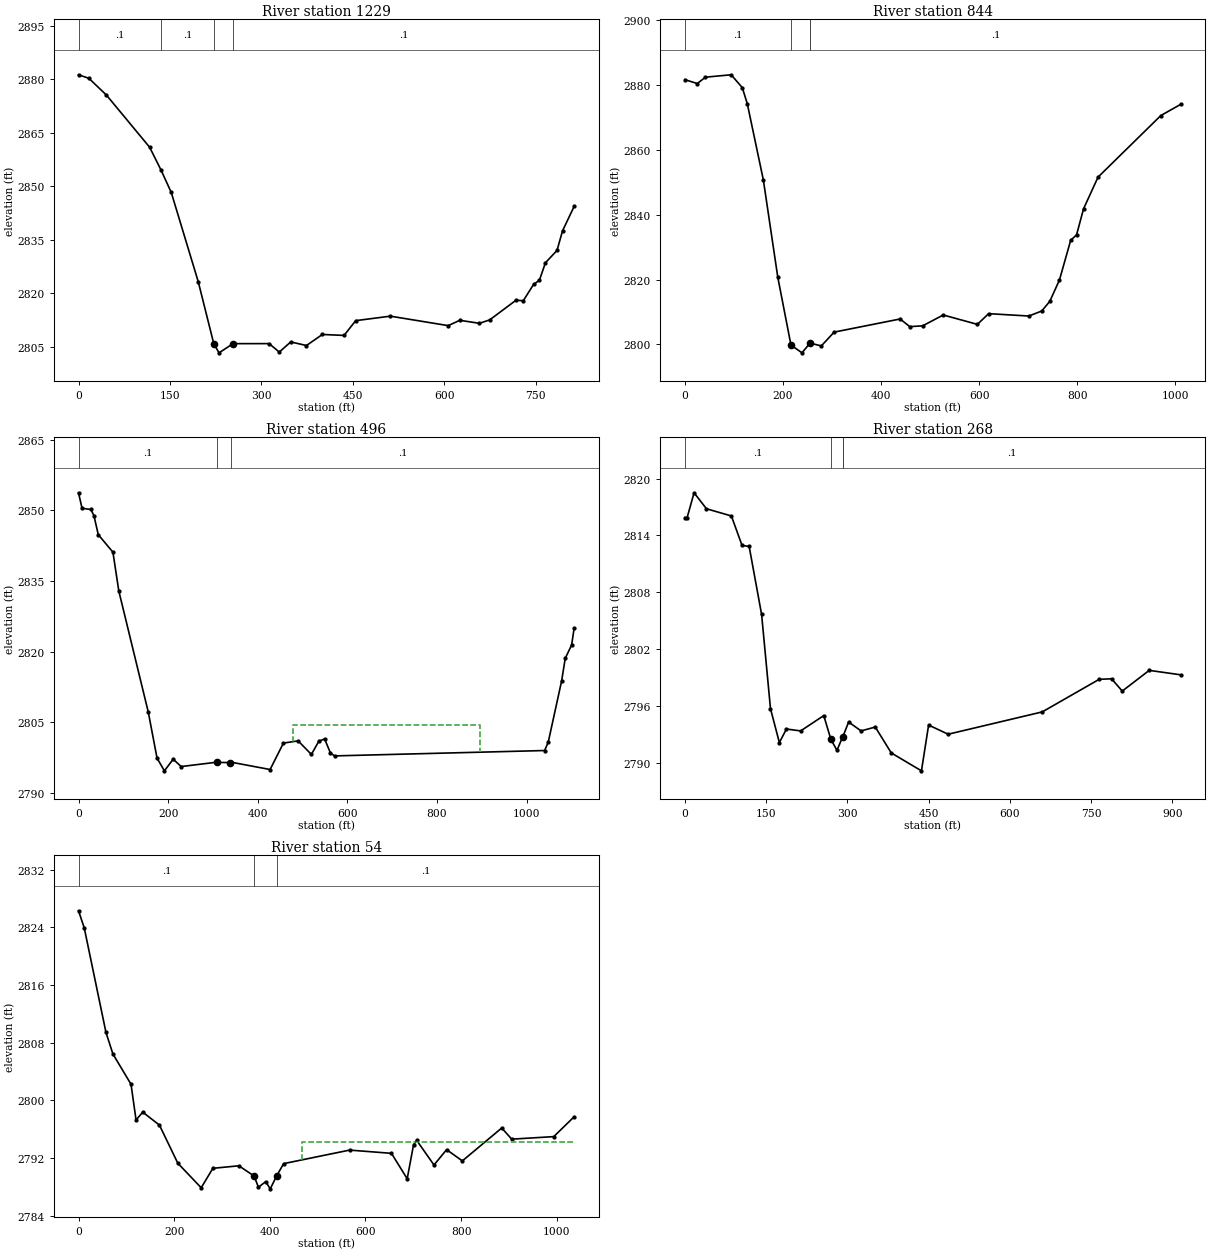
Type RM Length L Ch R = 1 ,1229    ,384.3,384.3,384.3
XS GIS Cut Line= 2
2088910.26763164362225.9704813022089612.90551238362634.869010477
#Sta/Elev= 30
       0 2881.31      17 2880.32    45.8 2875.61   116.7 2860.95  135.392854.535
   152.1 2848.28   196.5 2823.13   221.9 2805.76   230.5 2803.22   253.4  2805.8
   312.7 2805.81   329.3 2803.43   348.1 2806.28   373.9 2805.28     400 2808.38
   435.6 2808.11   454.6 2812.26   511.5 2813.52   606.4 2810.86   625.4 2812.36
   657.6 2811.51   674.4 2812.47   717.6 2817.99   729.6 2817.86   746.4 2822.43
     756  2823.6   765.8  2828.5   784.9 2831.99   793.9 2837.48     813 2844.36
#Mann= 4 ,-1 , 0
       0      .1       0  135.39      .1       0   221.9    .045       0
   253.4      .1       0
Bank Sta=221.9,253.4
XS Rating Curve= 0 ,0
Exp/Cntr=0.3,0.1

Type RM Length L Ch R = 1 ,844     ,347.8,347.8,347.8
XS GIS Cut Line= 2
2088779.17253645362716.547158469 2089789.7539791362685.160661675
#Sta/Elev= 30
       0 2881.63    25.2 2880.45    41.7 2882.41    94.2 2883.15   116.9 2879.19
   127.1 2874.23   159.9  2850.7   189.4 2820.66   216.2 2799.81   238.7 2797.41
     255  2800.4   255.1 2800.42   278.1 2799.54   304.3  2803.8   438.9 2807.85
   458.6 2805.49   484.9 2805.74   526.8 2809.08   596.5 2806.19   619.4 2809.49
   701.5 2808.76   727.8 2810.31   744.2 2813.29   763.9 2819.87   786.8 2832.11
   798.8 2833.79   813.1 2841.84   842.6 2851.59   970.7 2870.58  1011.1 2874.02
#Mann= 4 ,-1 , 0
       0      .1       0   216.2    .045       0     255    .045       0
   255.1      .1       0
Bank Sta=216.2,255
XS Rating Curve= 0 ,0
Exp/Cntr=0.3,0.1

Type RM Length L Ch R = 1 ,496     ,228.9,228.9,228.9
XS GIS Cut Line= 3
2088783.42563891363027.0778037682089636.25381382363033.949360781
2089859.36160442362913.623500785
#Sta/Elev= 30
       0  2853.7     7.9  2850.4    27.6 2850.16    34.4 2848.86    44.1 2844.81
    76.8  2841.1      90 2832.83   155.6 2807.21   175.3 2797.38   191.7 2794.69
   211.3 2797.16   229.1  2795.6   309.2 2796.53   310.1 2796.48   338.7 2796.44
   339.42796.548   427.6 2794.97   457.4 2800.58   490.2 2801.05   519.8 2798.17
   536.2 2800.95   549.3 2801.47   562.4 2798.45   571.4 2797.86  1040.4    2799
  1048.5 2800.81  1078.3 2813.77  1086.4 2818.57  1100.6 2821.39  1106.3    2825
#Mann= 3 ,-1 , 0
       0      .1       0   310.1    .045       0   339.4      .1       0
#XS Ineff= 1 ,-1
  478.82   896.3 2804.49
Permanent Ineff=
       F
Bank Sta=309.2,338.7
XS Rating Curve= 0 ,0
Exp/Cntr=0.3,0.1

Type RM Length L Ch R = 1 ,268     ,213.7,213.7,213.7
XS GIS Cut Line= 2
2088810.66461569363234.983079235     2089725.939      363227.824
#Sta/Elev= 30
       0 2815.89     3.7 2815.83    16.8 2818.51    39.7 2816.82    85.7 2816.06
   105.4 2812.94   118.5 2812.84   141.5 2805.65   157.9 2795.69   174.3 2792.11
   187.4 2793.54   213.6 2793.34   256.3 2794.96   269.4 2792.45   280.7 2791.29
   290.9 2792.67   292.4 2792.85   302.2 2794.28   325.2 2793.34   351.4 2793.75
     381 2791.01   436.7 2789.12   449.9 2793.96     486 2792.99   659.8 2795.35
   764.8 2798.79   787.8 2798.85   807.5 2797.55   857.3 2799.74   915.3 2799.27
#Mann= 4 ,-1 , 0
       0      .1       0   269.4    .045       0   290.9    .045       0
   292.4      .1       0
Bank Sta=269.4,290.9
XS Rating Curve= 0 ,0
Exp/Cntr=0.3,0.1

Type RM Length L Ch R = 1 ,54      ,54,54,54
XS GIS Cut Line= 4
2088681.61072109363412.5695717782088948.86989663363509.961635414
2089130.81043766363293.9848073392089598.24810418363250.679133696
#Sta/Elev= 30
       0 2826.32      12 2823.94    57.4 2809.43    71.9 2806.44   109.8 2802.23
   120.3 2797.27   134.3 2798.36   169.2 2796.56   207.6 2791.27   256.5 2787.86
   280.9 2790.56   335.3 2790.91   367.3 2789.48   376.1 2787.93   391.3 2788.71
   400.9 2787.71   414.5 2789.54   428.9 2791.21   566.8 2793.09   654.3 2792.64
   687.2 2789.11   700.4  2793.8     707 2794.45   743.2 2791.02   769.6 2793.15
   802.5 2791.59   884.9 2796.16   905.7 2794.61   993.6 2794.96  1036.3 2797.72
#Mann= 3 ,-1 , 0
       0      .1       0   367.3    .045       0   414.5      .1       0
#XS Ineff= 1 ,-1
  466.571036.288 2794.16
Permanent Ineff=
       F
Bank Sta=367.3,414.5
XS Rating Curve= 0 ,0
Exp/Cntr=0.3,0.1
LCMann Table=0

Chan Stop Cuts=-1
Use User Specified Reach Order=0
Composite Channel Slope=5